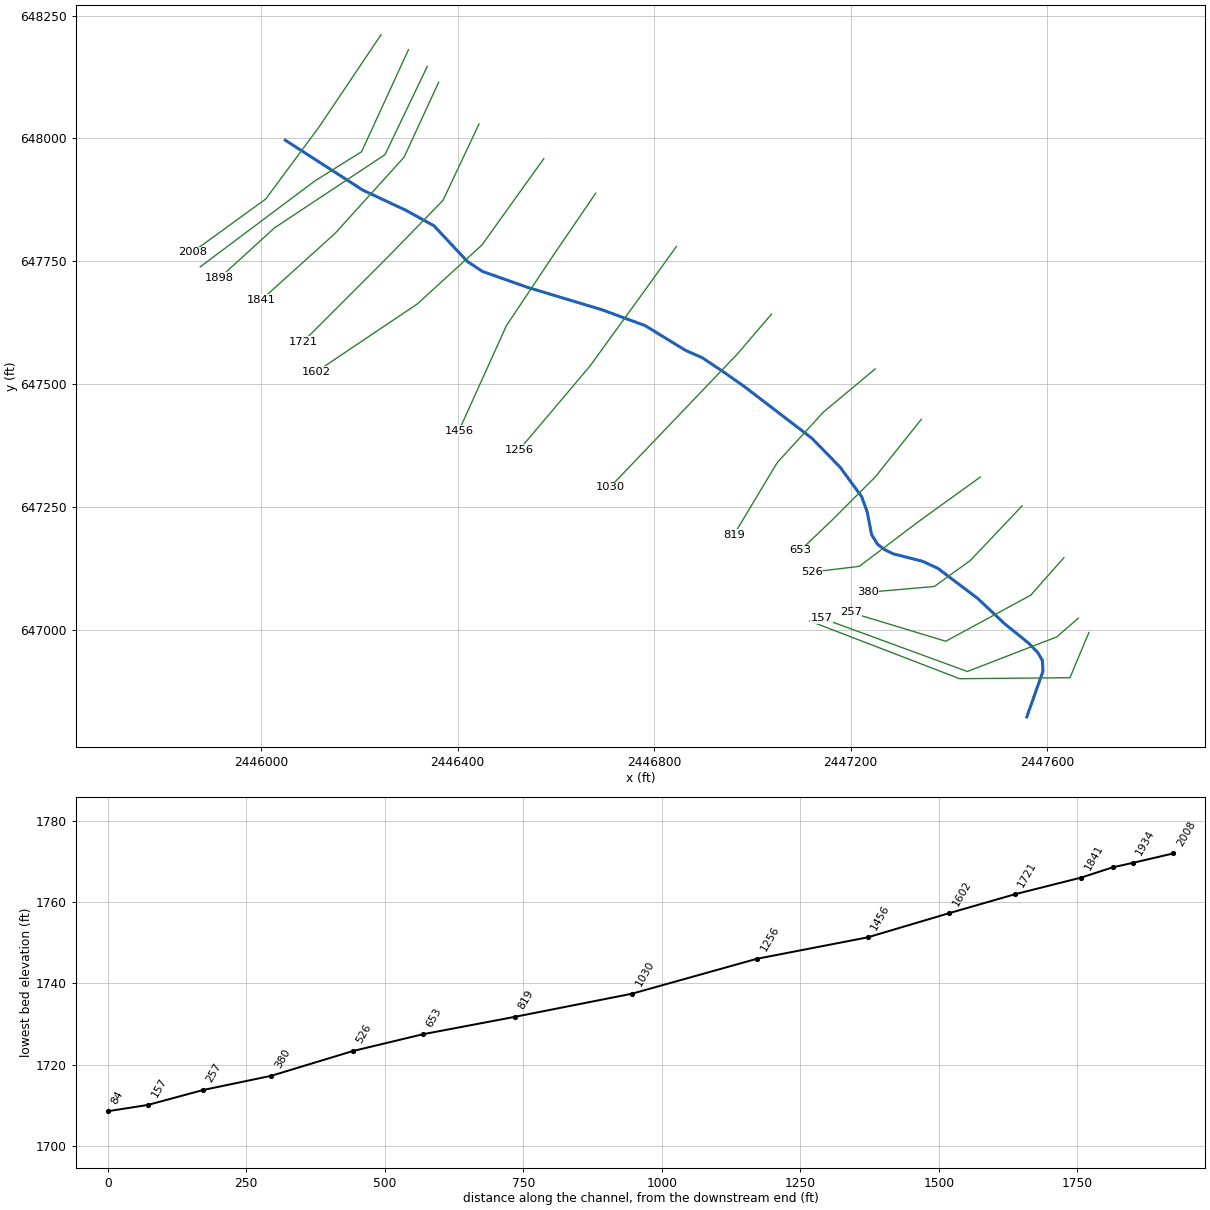
--- REEDSCK_T1.prj (project) ---

Proj Title=REEDSCK_T1
Current Plan=p01
Default Exp/Contr=0,0
English Units
Geom File=g01
Flow File=f01
Plan File=p01
Background Map Layer=QC
BEGIN DESCRIPTION:
Stream Name: Reeds Creek Tributary 1
Flood Zone: Zone A
Pendleton County, WV
WVDHSEM Flood Warning & Analysis Mapping
HEC-RAS Version: 5.0.7
Hydrology Method:
Regression
Model Notes:
Tie in with SReeds Creek at the downstream end.
END DESCRIPTION:
DSS Export Rating Curves= 0
DSS Export Rating Curve Sorted= 0
DSS Export Volume Flow Curves= 0
DXF OffsetX= 0
DXF OffsetY= 0
DXF ScaleX= 0
DXF ScaleY= 0

--- REEDSCK_T1.p01 (plan) ---

Plan Title=Floodplain
Program Version=5.07
Short Identifier=Floodplain
Geom File=g01
Flow File=f01
Subcritical Flow
K Sum by GR= 0
Std Step Tol= 0.01
Critical Tol= 0.01
Num of Std Step Trials= 20
Max Error Tol= 0.3
Flow Tol Ratio= 0.001
Split Flow NTrial= 30
Split Flow Tol= 0.02
Split Flow Ratio= 0.02
Log Output Level= 0
Friction Slope Method= 1
Unsteady Friction Slope Method= 2
Unsteady Bridges Friction Slope Method= 1
Parabolic Critical Depth
Global Vel Dist= 0 , 0 , 0
Global Log Level= 0
CheckData=True
Encroach Param=-1 ,0,0, 0
Mapping Interval=1HOUR
Computation Time Step Use Courant=        0
Computation Time Step Use Time Series=    0
Computation Time Step Count To Double=0
Computation Time Step Max Doubling=0
Computation Time Step Max Halving=0
Computation Time Step Residence Courant=0
Run HTab= 0
Run UNet= 0
Run Sediment= 0
Run PostProcess= 0
Run WQNet= 0
Run RASMapper= 0
UNET Theta= 0
UNET Theta Warmup= 0
UNET ZTol= 0
UNET ZSATol= 0
UNET MxIter= 0
UNET Max Iter WO Improvement= 0
UNET MaxInSteps= 0
UNET DtIC= 0
UNET DtMin= 0
UNET MaxCRTS= 0
UNET WFStab= 0
UNET SFStab= 0
UNET WFX= 1
UNET SFX= 1
UNET 1D Methodology=Finite Difference
UNET DSS MLevel= 1
UNET Pardiso=0
UNET DZMax Abort= 0
UNET Use Existing IB Tables= 0
UNET Froude Reduction=False
UNET Froude Limit= 0
UNET Froude Power= 0
UNET D1 Cores= 0
UNET D2 Coriolis=0
UNET D2 Cores= 0
UNET D2 Theta= 1
UNET D2 Theta Warmup= 1
UNET D2 Z Tol= 0.01
UNET D2 Volume Tol= 0.01
UNET D2 Max Iterations= 20
UNET D2 Equation= 0
UNET D2 RampUpFraction=0.1
UNET D2 TimeSlices= 1
UNET D2 BCVolumeCheck=0
UNET D1D2 MaxIter= 0
UNET D1D2 ZTol=0.01
UNET D1D2 QTol=0.1
UNET D1D2 MinQTol=1
Write IC File= 0
Write IC File at Fixed DateTime=0
Write IC File at Sim End=0
Echo Input=False
Echo Parameters=False
Echo Output=False
Write Detailed= 0
HDF Write Warmup=0
HDF Write Time Slices=0
HDF Flush=0
HDF Face Node Velocities=0
HDF Compression= 1
HDF Chunk Size= 1
HDF Spatial Parts= 1
HDF Use Max Rows=0
HDF Fixed Rows= 1
Calibration Method= 0
Calibration Iterations= 20
Calibration Max Change=0.05
Calibration Tolerance=0.2
Calibration Maximum=1.5
Calibration Minimum=0.5
Calibration Optimization Method= 1
WQ AD Non Conservative
WQ ULTIMATE=-1
WQ Max Comp Step=1HOUR
WQ Output Interval=15MIN
WQ Output Selected Increments= 0
WQ Output face flow=0
WQ Output face velocity=0
WQ Output face area=0
WQ Output face dispersion=0
WQ Output cell volume=0
WQ Output cell surface area=0
WQ Output cell continuity=0
WQ Output cumulative cell continuity=0
WQ Output face conc=0
WQ Output face dconc_dx=0
WQ Output face courant=0
WQ Output face peclet=0
WQ Output face adv mass=0
WQ Output face disp mass=0
WQ Output cell mass=0
WQ Output cell source sink temp=0
WQ Output nsm pathways=0
WQ Output nsm derived pathways=0
WQ Output MaxMinRange=-1
WQ Daily Max Min Mean=-1
WQ Daily Range=0
WQ Daily Time=0
WQ Create Restart=0
WQ Fixed Restart=0
WQ System Summary=0
WQ Write To DSS=0
WQ Use Fixed Temperature=0
Sorting and Armoring Iterations= 10
XS Update Threshold= 0.02
Bed Roughness Predictor= 0
Hydraulics Update Threshold= 0.02
Energy Slope Method= 1
Volume Change Method= 1
Sediment Retention Method= 0
XS Weighting Method= 0
Number of US Weighted Cross Sections= 1
Number of DS Weighted Cross Sections= 1
Upstream XS Weight=0
Main XS Weight=1
Downstream XS Weight=0
Number of DS XS's Weighted with US Boundary= 1
Upstream Boundary Weight= 1
Weight of XSs Associated with US Boundary= 0
Number of US XS's Weighted with DS Boundary= 1
Downstream Boundary Weight= 0.5
Weight of XSs Associated with DS Boundary= 0.5
Percentile Method= 0
Sediment Output Level= 3
Mass or Volume Output= 0
Output Increment Type= 1
Profile and TS Output Increment= 1
XS Output Flag= 0
XS Output Increment= 10
Write Gradation File= 0
Read Gradation Hotstart= 0
Write HDF5 File= 1
Write Binary Output= 1
Write DSS Sediment File= 0
SV Curve= 0
Specific Gage Flag= 0

--- REEDSCK_T1.f01 (steady flow) ---

Flow Title=Flows
Program Version=5.07
Number of Profiles= 6
Profile Names=P100yr,P10yr,P25yr,P50yr,P500yr,P101yr
River Rch & RM=REEDSCK_T1,Main            ,2008
     451     212     299     373     659     549
River Rch & RM=REEDSCK_T1,Main            ,1456
     586     274     387     484     859     713
Boundary for River Rch & Prof#=REEDSCK_T1,Main            , 1
Up Type= 0
Dn Type= 3
Dn Slope=0.02228
Boundary for River Rch & Prof#=REEDSCK_T1,Main            , 2
Up Type= 0
Dn Type= 3
Dn Slope=0.02228
Boundary for River Rch & Prof#=REEDSCK_T1,Main            , 3
Up Type= 0
Dn Type= 3
Dn Slope=0.02228
Boundary for River Rch & Prof#=REEDSCK_T1,Main            , 4
Up Type= 0
Dn Type= 3
Dn Slope=0.02228
Boundary for River Rch & Prof#=REEDSCK_T1,Main            , 5
Up Type= 0
Dn Type= 3
Dn Slope=0.02228
Boundary for River Rch & Prof#=REEDSCK_T1,Main            , 6
Up Type= 0
Dn Type= 3
Dn Slope=0.02228
DSS Import GetInterval= 0
DSS Import GetPeak= 0
DSS Import FillOption= 0

--- REEDSCK_T1.g01 (geometry) ---

Geom Title=Geometry
Program Version=5.07

River Reach=REEDSCK_T1      ,Main
Reach XY= 30
     2446049.083      647996.416      2446206.98       647894.79
      2446294.45      647853.837      2446351.91      647822.123
     2446419.749      647749.601     2446450.635      647729.265
     2446542.831      647696.722     2446693.814       647651.24
     2446781.636      647619.005     2446864.156      647568.435
     2446897.897      647553.675     2446939.371      647526.062
     2446983.867      647494.769     2447121.187        647389.7
     2447178.815      647330.615     2447222.639      647270.549
     2447233.988      647239.194     2447242.633      647193.894
     2447254.719      647174.058      2447270.18      647162.355
     2447286.291      647154.486     2447346.639      647139.119
     2447377.711      647124.772     2447458.509       647063.77
      2447513.67      647011.929      2447562.48      646972.467
      2447581.45      646952.861     2447590.612      646936.907
     2447591.709      646915.346     2447558.723      646822.131

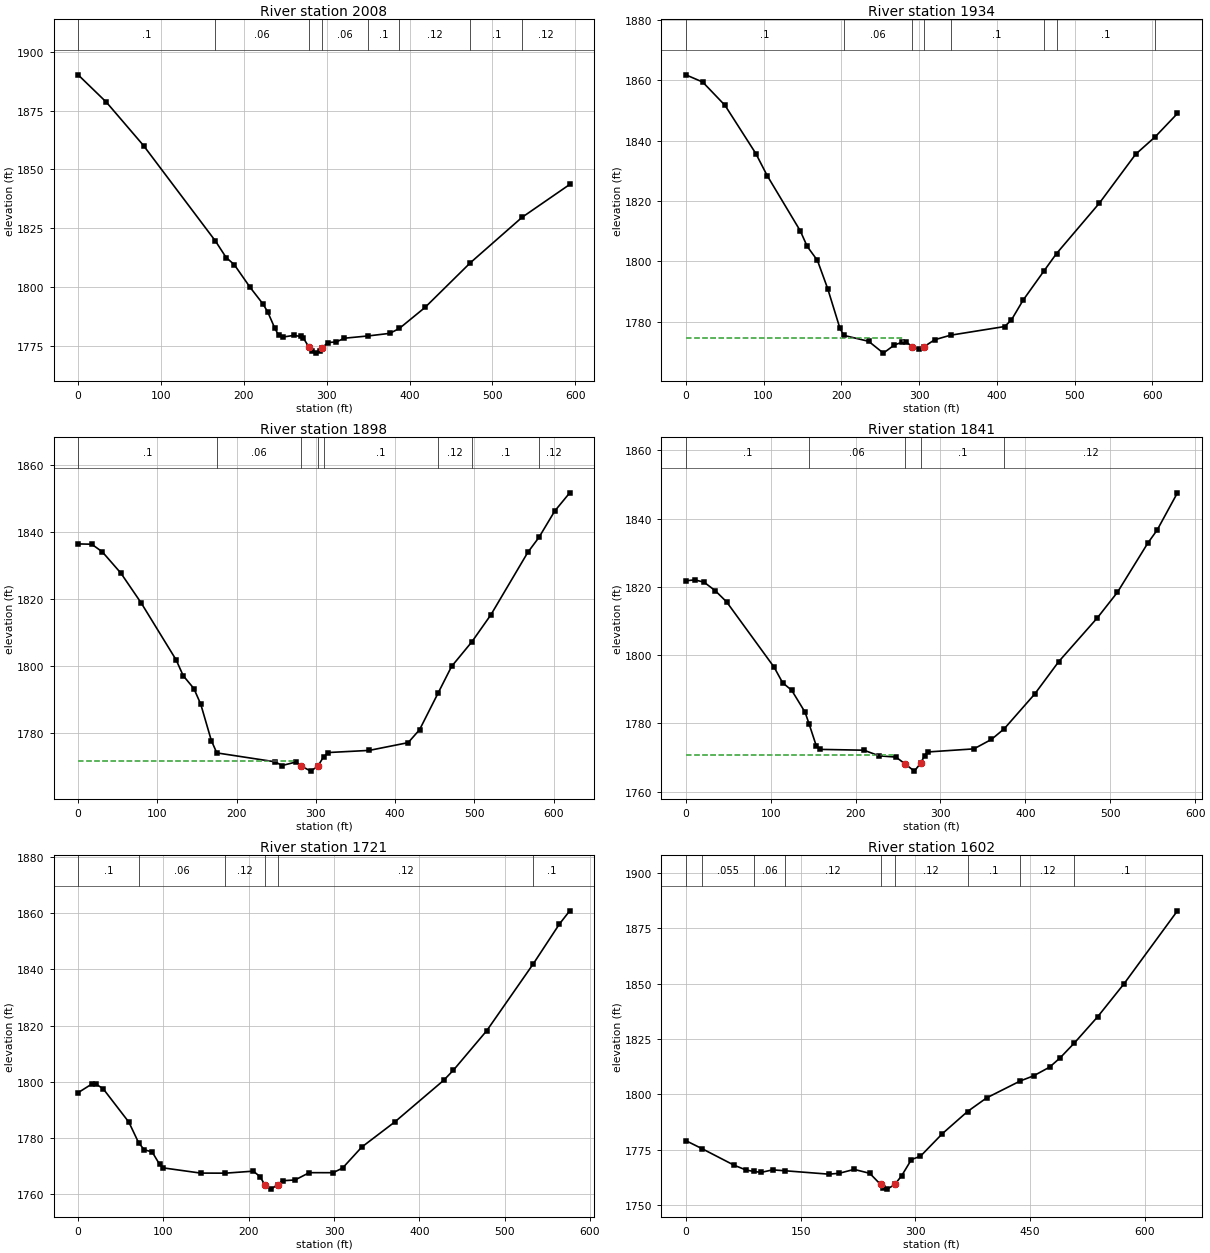
Type RM Length L Ch R = 1 ,2008    ,78.1,73.7,69.9
XS GIS Cut Line= 4
2446243.97037312648211.2362029772446117.84021364648023.507593514
2446009.30961129647876.8446173712445859.71337563647768.314015024
#Sta/Elev= 30
       0 1890.21    34.1 1878.59      79 1860.14  165.761819.594   178.7 1812.58
   188.4 1809.61   207.6 1799.92   223.1 1792.88   228.8 1789.53   237.4 1782.57
   241.9 1779.65   246.8 1778.79   260.3 1779.51   268.9 1779.05   271.7 1778.47
   278.81774.435   281.7 1772.91   286.6 1771.98   291.6 1772.84   294.6 1774.29
   301.6 1776.49   311.5 1776.73   321.5 1778.32  350.131779.284   376.2 1780.38
  387.74 1782.47   418.8 1791.41  473.541810.404  535.911829.685   593.4 1843.64
#Mann= 8 ,-1 , 0
       0      .1       0  165.76     .06       0   278.8    .045       0
   294.6     .06       0  350.13      .1       0  387.74     .12       0
  473.54      .1       0  535.91     .12       0
Bank Sta=278.8,294.6
XS Rating Curve= 0 ,0
Exp/Cntr(USF)=0,0
Exp/Cntr=0.5,0.3

Type RM Length L Ch R = 1 ,1934    ,36.6,36.2,37
XS GIS Cut Line= 4
2446299.78540297648180.723503783 2446204.3641274647972.970853161
2446109.54678394647913.7855050192445875.89032355647738.652513722
#Sta/Elev= 30
       0 1861.81    21.7 1859.42    50.4  1851.7    90.1 1835.72   104.7 1828.41
   147.3  1810.1   156.1    1805   169.3 1800.34   182.5    1791   198.2 1777.89
  203.251775.516   235.2 1773.55   254.1 1769.64   268.2 1772.33   277.7 1773.19
   283.6 1773.27  291.38 1771.79   300.5 1771.07     306 1771.69   320.1 1774.07
  340.521775.576   410.2 1778.45   418.9 1780.66   433.9 1787.19  460.671796.842
  476.841802.616     532 1819.32   578.6  1835.5   603.8 1841.28   632.4 1849.01
#Mann= 8 ,-1 , 0
       0      .1       0  203.25     .06       0  291.38    .045       0
     306     .06       0  340.52      .1       0  460.67     .12       0
  476.84      .1       0   603.8     .12       0
#XS Ineff= 2 , 0
          279.29 1774.67
Permanent Ineff=
       F       F
Bank Sta=291.38,306
XS Rating Curve= 0 ,0
Exp/Cntr(USF)=0,0
Exp/Cntr=0.5,0.3

Type RM Length L Ch R = 1 ,1898    ,53.7,56.6,58.6
XS GIS Cut Line= 4
 2446338.0282913648146.4955836222446252.16659238647967.196153511
2446027.41096872647818.2008524332445915.03315689647715.924416948
#Sta/Elev= 30
       0 1836.49    17.2  1836.4    30.6  1834.1    53.9 1827.77    79.4 1818.91
   123.7  1801.8   132.6 1797.09   146.1 1793.23   154.8 1788.52   168.1 1777.69
  175.021773.991   248.5 1771.33   257.3 1770.21   275.1 1771.28   281.21770.122
   293.5 1768.54   302.4 1769.98  309.731772.809   315.7  1774.1   367.4 1774.74
   416.5 1777.06   430.9 1780.93  454.461791.971   471.3 1799.85  496.86  1807.2
   520.9 1815.29   567.5 1833.97  581.611838.462   601.5 1846.33   620.4 1851.77
#Mann= 8 ,-1 , 0
       0      .1       0  175.02     .06       0   281.2    .045       0
   302.4     .06       0  309.73      .1       0  454.46     .12       0
  496.86      .1       0  581.61     .12       0
#XS Ineff= 2 , 0
           272.1 1771.61
Permanent Ineff=
       F       F
Bank Sta=281.2,302.4
XS Rating Curve= 0 ,0
Exp/Cntr(USF)=0,0
Exp/Cntr=0.5,0.3

Type RM Length L Ch R = 1 ,1841    ,120.1,120.3,116.5
XS GIS Cut Line= 4
2446361.30075404648114.4386387232446290.90252549647961.909143534
2446150.10606839647806.4463888222446000.50983273 647671.51645077
#Sta/Elev= 30
       0 1821.79    10.6 1822.06    21.5 1821.38    34.7 1818.88      48 1815.63
   104.1 1796.45     114 1791.94   124.8 1789.69   140.5 1783.28  145.061779.979
   153.7 1773.44   158.1  1772.4   209.8 1772.16   227.8 1770.51   247.6 1770.14
     258 1768.21   269.2 1766.03   276.61768.318   281.4  1770.6   285.4 1771.65
   339.4 1772.55     360 1775.31  375.091778.425     411  1788.6   439.3  1798.1
     485 1810.98   508.5 1818.42   544.3 1832.83   555.4  1836.7   579.2 1847.56
#Mann= 5 ,-1 , 0
       0      .1       0  145.06     .06       0     258    .045       0
   276.6      .1       0  375.09     .12       0
#XS Ineff= 2 , 0
          245.09 1770.66
Permanent Ineff=
       F       F
Bank Sta=258,276.6
XS Rating Curve= 0 ,0
Exp/Cntr(USF)=0,0
Exp/Cntr=0.3,0.1

Type RM Length L Ch R = 1 ,1721    ,119,118.5,117.4
XS GIS Cut Line= 4
2446443.43202068648029.3741125592446370.10053261647873.911357848
2446258.63667074647759.5142364562446085.57435889647586.451924607
#Sta/Elev= 30
       0 1796.18      16 1799.24    20.4 1799.32    29.3  1797.6    59.5  1785.7
   70.921778.394    77.5 1775.89    86.8 1775.12    95.5 1770.71     100 1769.44
   143.6  1767.6  172.731767.574   205.4 1768.29   213.2 1766.36   218.8 1763.49
   226.4  1761.9     234 1763.54   239.7 1764.89   254.3 1765.15     271 1767.75
     299 1767.74   310.1  1769.4   332.5 1776.83   371.1 1785.73   428.7  1800.6
     440 1804.17   479.1 1818.21   533.71841.986   564.4 1856.16   576.4 1860.81
#Mann= 6 ,-1 , 0
       0      .1       0   70.92     .06       0  172.73     .12       0
   218.8    .045       0     234     .12       0   533.7      .1       0
Bank Sta=218.8,234
XS Rating Curve= 0 ,0
Exp/Cntr(USF)=0,0
Exp/Cntr=0.3,0.1

Type RM Length L Ch R = 1 ,1602    ,143.8,146.8,150
XS GIS Cut Line= 4
2446575.42869921647958.9758840112446449.29853972647782.980312639
2446317.30186119647662.7166722012446111.97369459647524.853474627
#Sta/Elev= 30
       0 1779.13   20.981775.536      63 1768.05    78.8 1765.86   88.831765.225
    98.5  1764.8   113.3 1765.94  130.251765.521   186.9    1764   200.3 1764.39
     220 1766.15   240.4 1764.37  254.51 1759.34   258.2 1757.68   263.3 1757.25
  273.03 1759.34     282 1763.27   294.8 1770.59   306.6 1772.09   335.4 1782.33
  368.091792.264   393.1 1798.42  437.231806.085   454.5 1808.37   475.3 1812.28
   489.1 1816.47  507.881823.242   538.1 1834.99   572.6 1849.89   642.4 1882.81
#Mann= 9 ,-1 , 0
       0      .1       0   20.98    .055       0   88.83     .06       0
  130.25     .12       0  254.51    .045       0  273.03     .12       0
  368.09      .1       0  437.23     .12       0  507.88      .1       0
Bank Sta=254.51,273.03
XS Rating Curve= 0 ,0
Exp/Cntr(USF)=0,0
Exp/Cntr=0.3,0.1

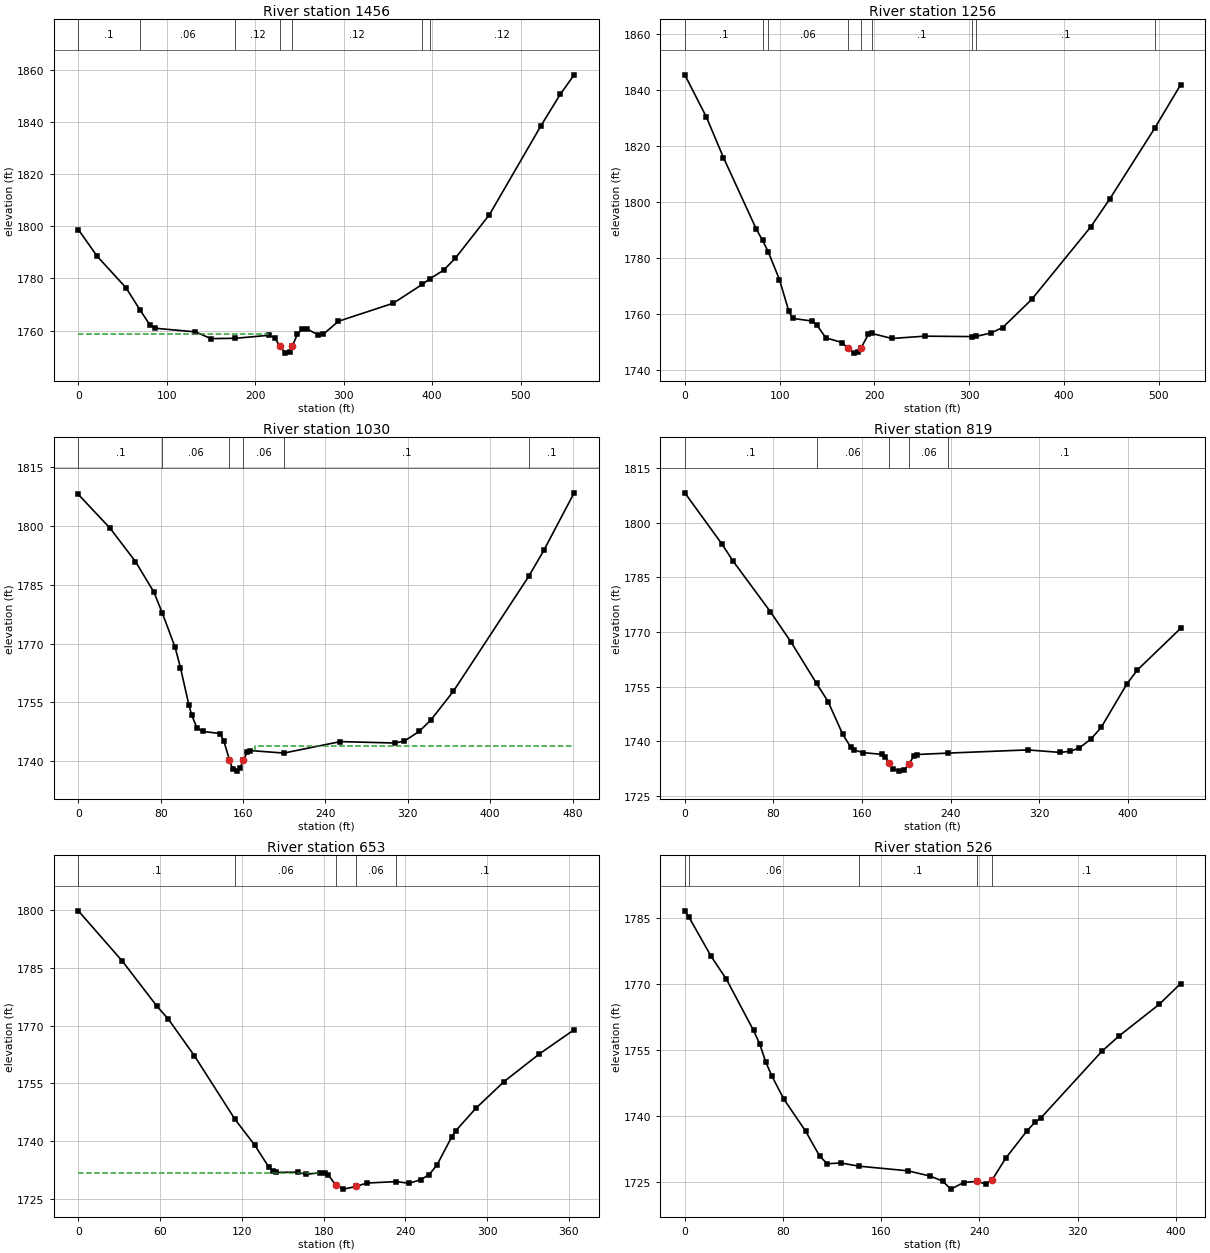
Type RM Length L Ch R = 1 ,1456    ,201.2,199.8,200
XS GIS Cut Line= 4
2446681.02604203647888.5776554622446593.02825634647759.514236456
2446499.16395161647618.7177793582446402.36638736647404.589834189
#Sta/Elev= 30
       0 1798.81    21.4  1788.5    53.8 1776.46   69.671767.935    80.6  1762.3
    86.3 1760.89   132.4 1759.48   149.9 1756.89  177.591757.008     216 1758.18
   221.8 1757.19   227.5 1754.21   233.9 1751.31   238.7 1751.68     242 1754.12
   247.7 1758.71   253.1 1760.47   257.9 1760.73   270.8 1758.34   276.6 1758.48
   293.9 1763.55     356  1770.5  388.661777.717  397.121779.836     413 1783.23
   426.2 1787.82   464.7 1804.56   522.8 1838.66   544.7  1850.8   560.4 1858.28
#Mann= 7 ,-1 , 0
       0      .1       0   69.67     .06       0  177.59     .12       0
   227.5    .045       0     242     .12       0  388.66      .1       0
  397.12     .12       0
#XS Ineff= 2 , 0
          214.69 1758.48
Permanent Ineff=
       F       F
Bank Sta=227.5,242
XS Rating Curve= 0 ,0
Exp/Cntr(USF)=0,0
Exp/Cntr=0.3,0.1

Type RM Length L Ch R = 1 ,1256    ,225.4,225.2,223
XS GIS Cut Line= 4
2446845.28857531647780.0470531162446777.82360628647686.182748384
2446669.29300394647536.5865127182446525.56328732647366.457460392
#Sta/Elev= 30
       0 1845.46    22.7 1830.44    40.8 1815.89    75.3 1790.43   82.021786.335
   87.911782.317    99.9 1772.28   109.8 1760.95     114 1758.43   134.5  1757.5
   139.4 1756.03   148.8 1751.49     166 1749.83   171.81747.767     179 1746.04
   183.2 1746.52     186 1747.98   193.8 1752.79  197.441753.067   218.5 1751.27
   253.1  1752.1  302.64 1751.95  307.311752.018     323 1753.24   335.4 1755.19
   365.9  1765.2   428.3 1791.15   448.2 1801.05  495.571826.291   523.1  1841.9
#Mann= 9 ,-1 , 0
       0      .1       0   82.02    .055       0   87.91     .06       0
   171.8    .045       0     186     .06       0  197.44      .1       0
  302.64     .12       0  307.31      .1       0  495.57      .1       0
#XS Ineff= 2 , 0
                          197.43         1753.05
Permanent Ineff=
       F       F
Bank Sta=171.8,186
XS Rating Curve= 0 ,0
Exp/Cntr(USF)=0,0
Exp/Cntr=0.3,0.1

Type RM Length L Ch R = 1 ,1030    ,211.5,211.2,211.4
XS GIS Cut Line= 4
2447038.88370382647642.1838555412446968.48547527647560.052588901
2446839.42205626647425.1226508492446710.35863726647290.192712797
#Sta/Elev= 30
       0 1808.03    30.9 1799.39    55.5 1790.91    73.4 1783.11   81.671777.704
    93.9 1769.12    99.2 1763.83   107.4 1754.29   110.2 1751.69   115.3 1748.41
   120.9 1747.59   137.5 1747.04   141.3 1745.19  146.76 1740.31   149.8 1738.07
   154.1 1737.45     157 1738.26  160.34 1740.27     164 1742.26   166.8  1742.7
  199.631742.057   254.5 1744.98   307.4 1744.62   316.8 1745.13   331.2 1747.61
   342.2 1750.42   364.4 1757.86  437.461787.121   452.1 1793.75   481.6 1808.44
#Mann= 6 ,-1 , 0
       0      .1       0   81.67     .06       0  146.76    .045       0
  160.34     .06       0  199.63      .1       0  437.46      .1       0
#XS Ineff= 2 , 0
                          172.06         1743.87
Permanent Ineff=
       F       F
Bank Sta=146.76,160.34
XS Rating Curve= 0 ,0
Exp/Cntr(USF)=0,0
Exp/Cntr=0.3,0.1

Type RM Length L Ch R = 1 ,819     ,166.7,166.6,166.5
XS GIS Cut Line= 4
2447250.07838947647530.7199936722447144.48104664647442.722207986
2447050.61674191647340.0581246862446962.61895623647193.395148543
#Sta/Elev= 30
       0 1808.23    33.5 1794.16    43.5 1789.51    77.2 1775.59      96 1767.19
  118.911755.863   129.3 1750.89   142.6 1741.87   149.9 1738.32   152.7 1737.56
   161.2 1736.84   178.2 1736.35     181  1735.7  184.22 1733.89   187.5 1732.42
   193.4 1731.76     198 1732.04   202.3  1733.7   206.5 1735.79   209.3 1736.32
  237.861736.716   309.4 1737.59   338.6 1736.91   347.9  1737.2     356  1738.1
   366.6 1740.56   375.9 1743.78   399.2 1755.78   408.5 1759.53   447.6 1770.99
#Mann= 5 ,-1 , 0
       0      .1       0  118.91     .06       0  184.22    .045       0
   202.3     .06       0  237.86      .1       0
Bank Sta=184.22,202.3
XS Rating Curve= 0 ,0
Exp/Cntr(USF)=0,0
Exp/Cntr=0.3,0.1

Type RM Length L Ch R = 1 ,653     ,126,126.5,121.4
XS GIS Cut Line= 4
 2447343.9426942647428.0559103722447250.07838947647310.725529458
2447162.08060378647222.7277437722447097.54889428647161.129293791
#Sta/Elev= 30
       0 1799.87    32.2 1786.82    57.8    1775    65.9 1771.77    85.2 1762.15
  114.981745.619   129.6 1738.85   139.8 1733.18   142.8 1732.18   144.9 1731.81
     161 1731.88     167  1731.3   177.6 1731.74   180.8 1731.54   183.3 1731.21
     1891728.498   194.6 1727.46   204.11728.167   211.5 1729.04  233.171729.413
     243 1728.98   251.5 1729.96   257.5 1731.23   263.2 1733.72   274.1 1741.09
   276.9 1742.61   291.8 1748.51   312.5 1755.45   338.2 1762.59   363.9 1768.94
#Mann= 5 ,-1 , 0
       0      .1       0  114.98     .06       0     189    .045       0
   204.1     .06       0  233.17      .1       0
#XS Ineff= 2 , 0
          177.91 1731.75
Permanent Ineff=
       F       F
Bank Sta=189,204.1
XS Rating Curve= 0 ,0
Exp/Cntr(USF)=0,0
Exp/Cntr=0.3,0.1

Type RM Length L Ch R = 1 ,526     ,133.3,146.6,141.6
XS GIS Cut Line= 4
2447464.20633464647310.7255294582447338.07617515647219.794484249
2447217.81253471 647128.863439042447121.01497046647117.130400948
#Sta/Elev= 30
       0 1786.57    3.221785.214    21.5  1776.2    33.9 1771.02      56 1759.38
      61 1756.32    65.9 1752.23    70.8 1749.09    80.7 1743.76    98.4 1736.49
   109.8 1730.83     116 1729.09     127 1729.26  142.091728.532   181.4 1727.49
   199.8 1726.29   209.9 1725.16   216.7 1723.32     227 1724.82   237.91725.096
   244.9 1724.49   250.2 1725.36   261.3 1730.33   278.4 1736.47     285 1738.47
   289.9 1739.47   339.5  1754.6   353.9 1758.19   386.3  1765.3   403.8 1770.03
#Mann= 5 ,-1 , 0
       0      .1       0    3.22     .06       0  142.09      .1       0
   237.9    .045       0   250.2      .1       0
Bank Sta=237.9,250.2
XS Rating Curve= 0 ,0
Exp/Cntr(USF)=0,0
Exp/Cntr=0.3,0.1

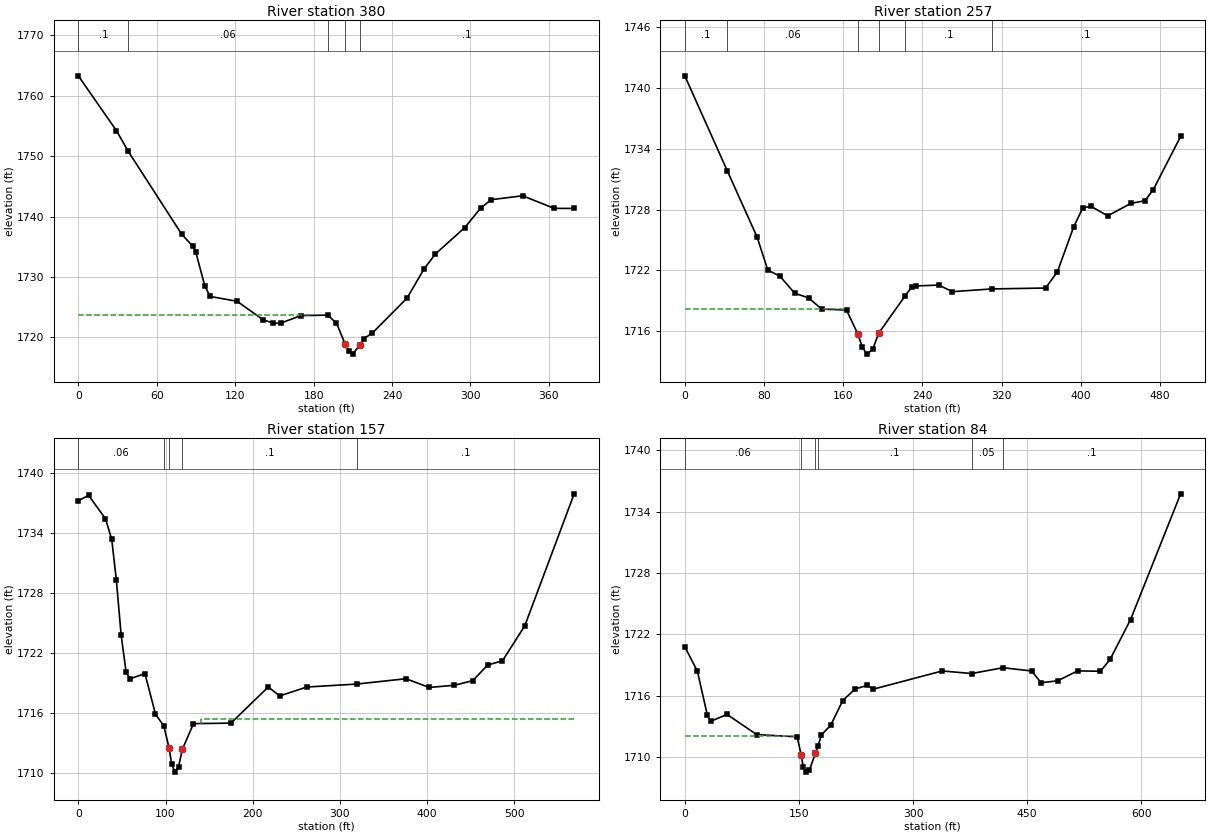
Type RM Length L Ch R = 1 ,380     ,127,123,121.3
XS GIS Cut Line= 4
 2447549.2708608   647252.0603392447443.67351797647140.596477131
 2447370.3420299 647087.797805722447235.41209185647076.064767628
#Sta/Elev= 30
       0 1763.26    29.2 1754.18   38.161750.784      79  1737.1    87.5  1735.1
    89.8 1734.17    96.7 1728.57   100.8 1726.79   121.5 1725.98   141.3 1722.94
   149.1 1722.37   154.7 1722.36   170.2 1723.62  190.681723.701   197.5 1722.38
     204 1718.99     207  1717.7   209.9 1717.25   215.6 1718.81   218.5 1719.82
   224.9 1720.73   251.5 1726.51   264.5 1731.34   273.2 1733.81   295.7 1738.18
   307.7 1741.36   315.8 1742.78   339.9 1743.43     364 1741.35379.3421 1741.33
#Mann= 5 ,-1 , 0
       0      .1       0   38.16     .06       0  190.68      .1       0
     204    .045       0   215.6      .1       0
#XS Ineff= 2 , 0
          178.37  1723.7
Permanent Ineff=
       F       F
Bank Sta=204,215.6
XS Rating Curve= 0 ,0
Exp/Cntr(USF)=0,0
Exp/Cntr=0.3,0.1

Type RM Length L Ch R = 1 ,257     ,99.8,99.9,98.5
XS GIS Cut Line= 4
2447634.33538696647146.4629961772447566.87041794647070.198248583
2447393.80810609646976.3339438512447200.21297758647034.999134308
#Sta/Elev= 30
       0  1741.2   43.111731.788    73.1 1725.29    83.9 1722.03      96 1721.45
   111.1 1719.75     125  1719.3   138.4 1718.19   163.4  1718.1   174.8 1715.74
   179.3 1714.47     184 1713.75   189.9 1714.22   195.8  1715.8   222.21719.439
   229.4 1720.39   233.9 1720.48   256.7 1720.56   270.3 1719.91  310.26 1720.18
   364.6 1720.27   376.5 1721.88     393 1726.32   402.2 1728.18   410.6 1728.32
   427.3 1727.39   450.8 1728.62   464.9 1728.88   473.3 1729.96500.9895 1735.22
#Mann= 6 ,-1 , 0
       0      .1       0   43.11     .06       0   174.8    .045       0
   195.8      .1       0   222.2      .1       0  310.26      .1       0
#XS Ineff= 2 , 0
          159.41 1718.24
Permanent Ineff=
       F       F
Bank Sta=174.8,195.8
XS Rating Curve= 0 ,0
Exp/Cntr(USF)=0,0
Exp/Cntr=0.3,0.1

Type RM Length L Ch R = 1 ,157     ,73.7,72.4,62.7
XS GIS Cut Line= 4
2447663.66798219647023.2660962172447619.66908935 646985.13372242
2447437.80699893646914.7354938712447141.54778712647023.266096217
#Sta/Elev= 30
       0 1737.21    11.8 1737.75    31.1 1735.41    38.3 1733.35    43.6 1729.29
    49.1 1723.78    54.8 1720.05    59.2  1719.4    76.4 1719.92    88.5 1715.87
   98.061714.689     104 1712.52   107.1 1710.87   110.7 1710.07     115 1710.61
   119.3 1712.35   132.1 1714.92   175.1 1714.97   217.9 1718.59   230.9 1717.69
     262 1718.58  319.181718.876   375.8 1719.41   402.3 1718.54   431.2 1718.75
   452.5 1719.22   469.5 1720.78   486.5  1721.2   512.1  1724.7568.7486  1737.9
#Mann= 5 ,-1 , 0
       0     .06       0   98.06      .1       0     104    .045       0
   119.3      .1       0  319.18      .1       0
#XS Ineff= 2 , 0
                           140.7         1715.36
Permanent Ineff=
       F       F
Bank Sta=104,119.3
XS Rating Curve= 0 ,0
Exp/Cntr(USF)=0,0
Exp/Cntr=0.3,0.1

Type RM Length L Ch R = 1 ,84      ,84,84,84
XS GIS Cut Line= 4
 2447685.2186399646994.1006967812447646.72840845646902.151810518
2447422.20205827646900.0134643262447116.41855279647017.622504895
#Sta/Elev= 30
       0 1720.78    16.5  1718.4    29.5 1714.14    33.8 1713.48    55.5 1714.16
    94.5 1712.19   147.7 1711.97   152.9 1710.23   155.7 1709.02   159.7 1708.52
   163.7 1708.69   171.7 1710.36  175.131711.072   179.7 1712.17   191.7 1713.09
   207.7 1715.52   223.7 1716.64   239.7    1717   247.7 1716.63   338.4 1718.41
  377.04 1718.16  418.271718.728     456 1718.41   468.4 1717.26   490.1 1717.45
   516.5 1718.42   546.5 1718.38   559.3 1719.57     586 1723.43651.8374 1735.73
#Mann= 6 ,-1 , 0
       0     .06       0   152.9    .045       0   171.7     .06       0
  175.13      .1       0  377.04     .05       0  418.27      .1       0
#XS Ineff= 2 , 0
          143.47 1712.01
Permanent Ineff=
       F       F
Bank Sta=152.9,171.7
XS Rating Curve= 0 ,0
Exp/Cntr(USF)=0,0
Exp/Cntr=0.3,0.1
LCMann Table=0

Chan Stop Cuts=-1
Use User Specified Reach Order=0
Composite Channel Slope=5